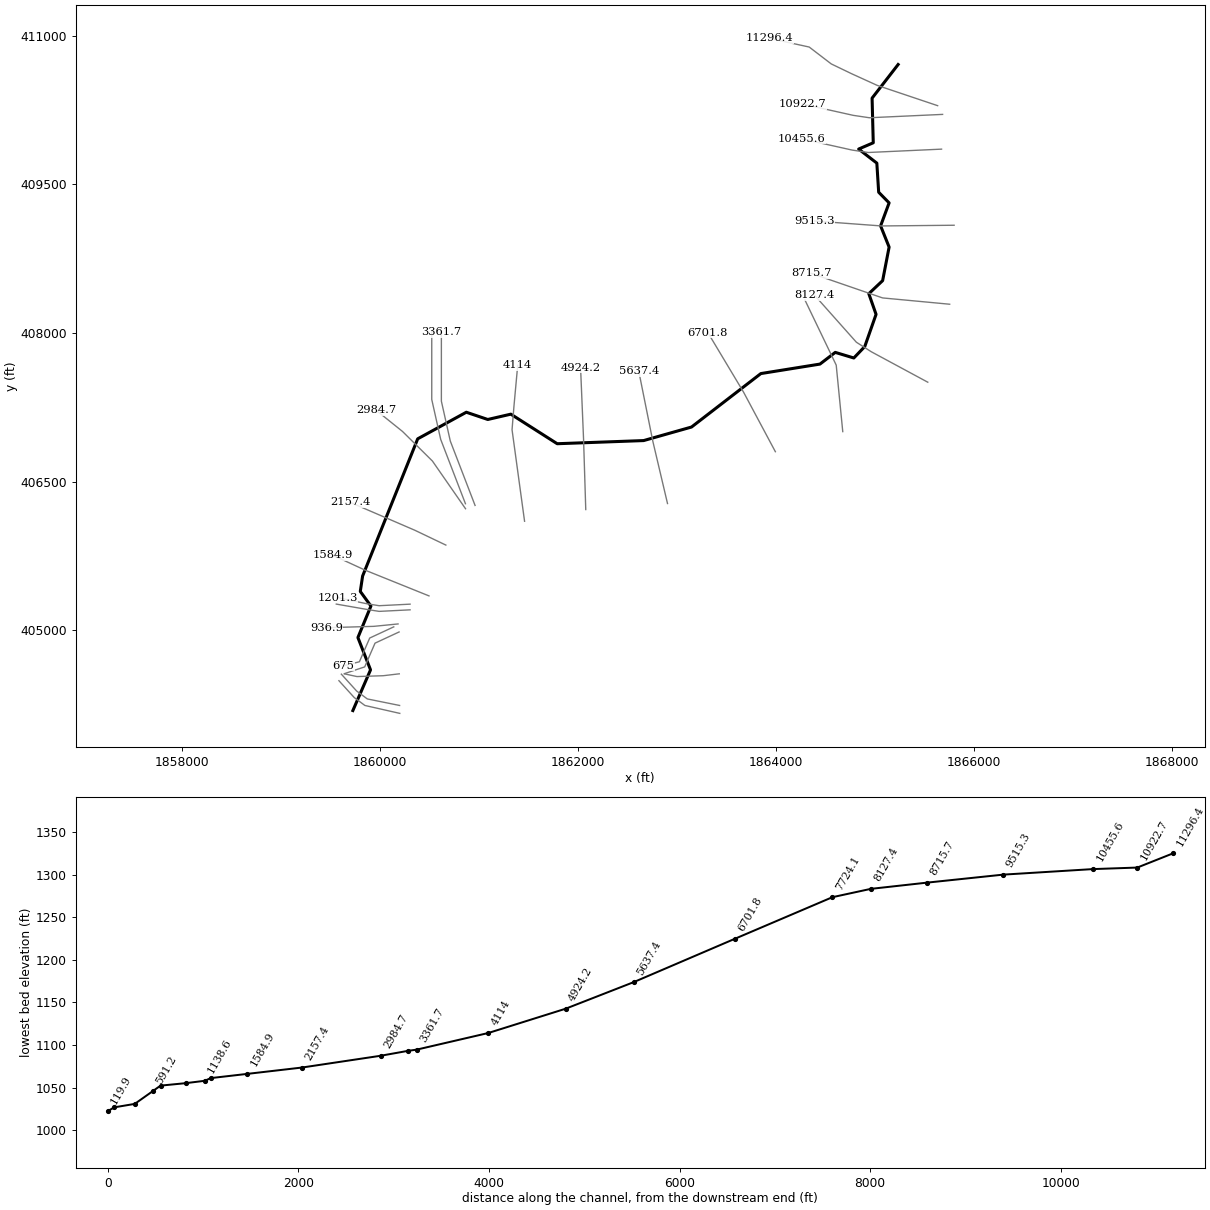
--- TibbsRun.prj (project) ---

Proj Title=TibbsRun
Current Plan=p01
Default Exp/Contr=0,0
English Units
Geom File=g01
Flow File=f01
Plan File=p01
BEGIN DESCRIPTION:
END DESCRIPTION:
DSS Export Rating Curves= 0
DSS Export Rating Curve Sorted= 0
DSS Export Volume Flow Curves= 0
DXF OffsetX= 0
DXF OffsetY= 0
DXF ScaleX= 0
DXF ScaleY= 0

--- TibbsRun.p01 (plan) ---

Plan Title=Floodplain
Program Version=4.00
Geom File=g01
Flow File=f01
K Sum by GR=0
Std Step Tol=0.01
Critical Tol=0.01
Num of Std Step Trials=20
Max Error Tol=0.3
Flow Tol Ratio=0.001
Split Flow NTrial=30
Split Flow Tol=0.02
Split Flow Ratio=0.02
Log Output Level=0
Friction Slope Method=1
Unsteady Friction Slope Method=2
Unsteady Bridges Friction Slope Method=1
Global Log Level=0
CheckData=False
Run HTab=0
Run UNet=0
Run PostProcess=0
UNET Theta=0
UNET Theta Warmup=0
UNET ZTol=0
UNET ZSATol=0
UNET MxIter=0
UNET MaxInSteps=0
UNET DtIC=0
UNET DtMin=0
UNET MaxCRTS=0
UNET WFStab=0
UNET SFStab=0
UNET WFX=0
UNET SFX=0
UNET DSS MLevel=0
UNET DZMax Abort=0
UNET Convert EG Bridges=0
UNET Use Existing IB Tables=0
UNET Froude Limit=0
UNET Froude Power=0
Write IC File=0
Echo Input=False
Echo Output=False
Write Detailed=0

--- TibbsRun.f01 (steady flow) ---

Flow Title=NFF Regression Equation
Program Version=4.10
Number of Profiles= 1
Profile Names=P100yr
River Rch & RM=TibbsRun,Main            ,11296.4
    1084
River Rch & RM=TibbsRun,Main            ,7724.1
    1165
River Rch & RM=TibbsRun,Main            ,6701.8
    1373
River Rch & RM=TibbsRun,Main            ,3361.7
    1469
River Rch & RM=TibbsRun,Main            ,2984.7
    1657
River Rch & RM=TibbsRun,Main            ,188.9
    1733
Boundary for River Rch & Prof#=TibbsRun,Main            , 1
Up Type= 0
Dn Type= 3
Dn Slope=0.01886
DSS Import GetInterval= 0
DSS Import GetPeak= 0
DSS Import FillOption= 0

--- TibbsRun.g01 (geometry) ---

Geom Title=USGS 10m DEM
Program Version=4.10

River Reach=TibbsRun        ,Main
Reach XY= 30
      1865230.32      410709.157     1864967.244       410369.77
     1864979.064      409919.151     1864831.609      409855.677
     1865015.196       409713.69     1865033.749      409419.951
     1865139.214      409312.533      1865053.28      409080.315
     1865139.214      408866.456     1865073.787      408527.602
     1864934.144      408395.771     1865007.383      408187.185
      1864893.13      407862.002     1864782.782      407746.772
     1864595.094      407803.411     1864440.803      407685.251
     1863843.756      407589.552     1863143.489      407049.924
     1862659.914       406913.21     1861786.705      406881.429
     1861318.461      407179.801     1861085.462      407126.093
     1860868.673      407199.332     1860377.579      406930.787
     1859821.252      405545.684     1859797.815      405390.416
     1859905.233      405242.961     1859773.722      404925.011
     1859901.263      404598.845      1859722.77       404187.91

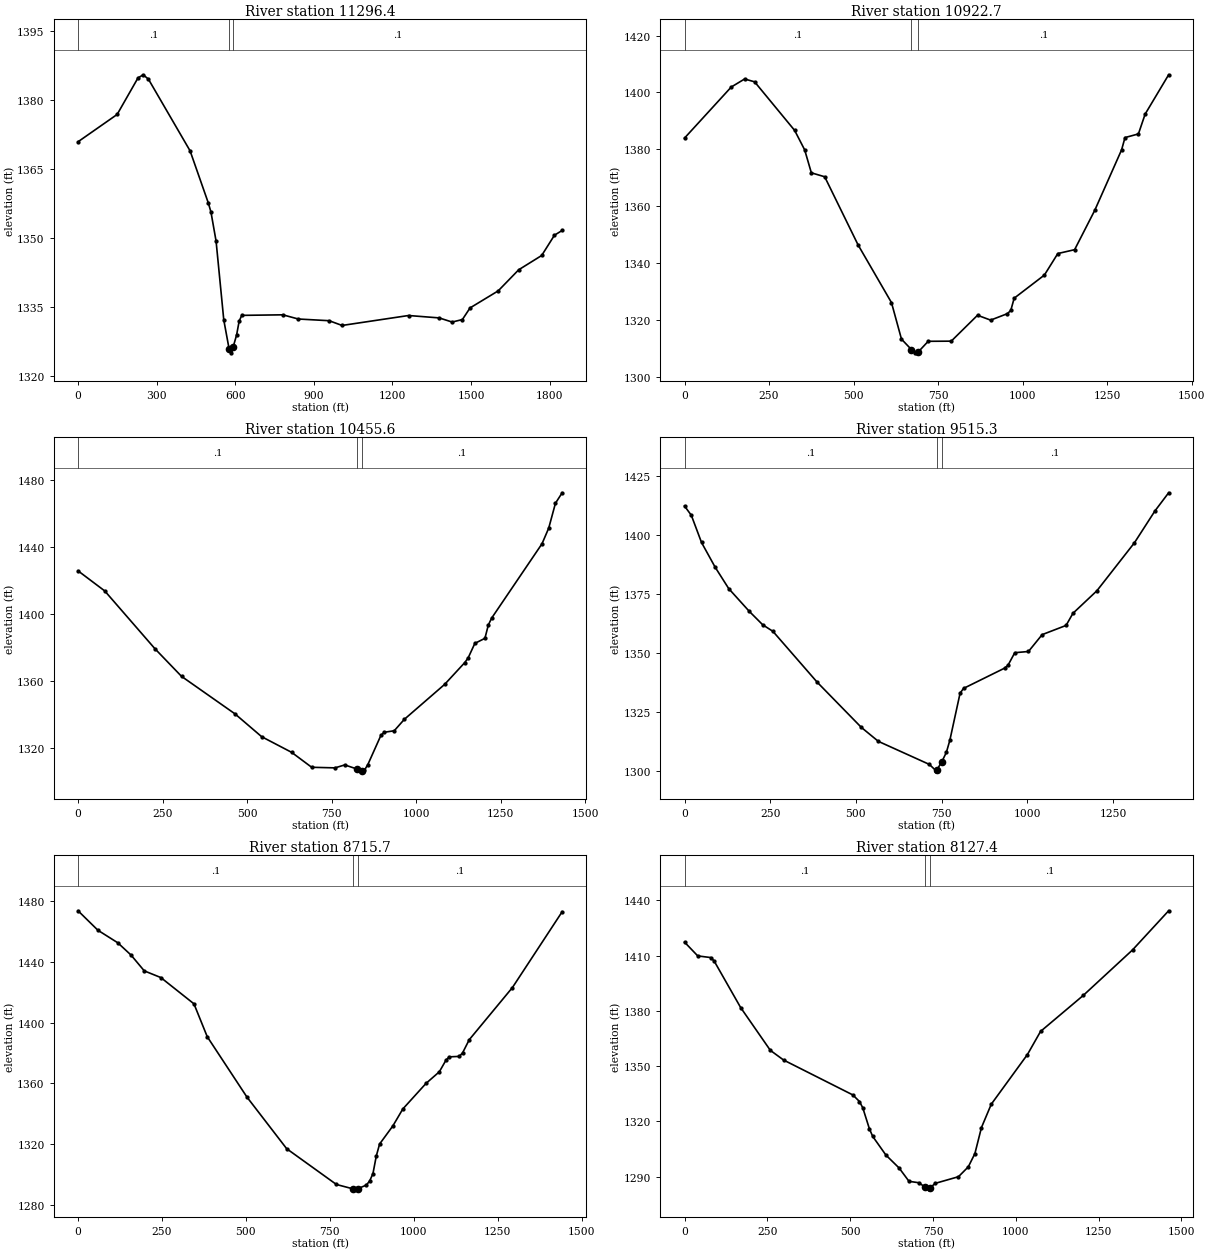
Type RM Length L Ch R = 1 ,11296.4 ,364.9,373.7,379.4
XS GIS Cut Line= 6
     1865629.288      410293.653     1865018.518      410498.682
     1864759.496       410616.57      1864554.99      410714.935
     1864332.161       410885.45     1863931.371       410973.34
#Sta/Elev= 30
       0 1370.89   149.2 1376.82   228.8 1384.76   248.7 1385.44   268.6 1384.49
   427.7 1368.91   497.4 1357.57   507.3 1355.64   526.9 1349.31   556.3 1332.18
     577 1325.77   585.7 1325.03     592 1326.28   605.2 1328.89     615 1331.91
   624.8 1333.17   781.8 1333.29   840.7 1332.38   958.6 1332.01  1007.9 1330.98
  1261.6 1333.14  1378.6 1332.62    1428 1331.72  1467.2 1332.26  1496.5 1334.79
  1603.9 1338.49  1682.1 1343.07    1770 1346.18  1818.8 1350.59  1848.2 1351.62
#Mann= 3 , 0 , 0
       0      .1       0     577    .045       0     592      .1       0
Bank Sta=577,592
XS Rating Curve= 0 ,0
Exp/Cntr=0.3,0.1

Type RM Length L Ch R = 1 ,10922.7 ,474.1,467.1,463.6
XS GIS Cut Line= 4
     1865679.375      410205.613     1864939.738       410171.74
     1864776.543      410196.046     1864262.655      410310.629
#Sta/Elev= 30
       0 1383.96   138.2 1401.92   177.7 1404.75   207.3 1403.75   325.8 1386.64
   355.4  1379.8   375.1 1371.74   414.6 1370.35   513.4 1346.36   612.1 1326.09
   641.7 1313.23   671.3 1309.54   681.2 1308.41     691 1308.69   720.7 1312.47
   788.9 1312.52   866.6 1321.63   905.4 1319.92   955.1  1322.2     965 1323.33
     975 1327.63  1064.4 1335.77  1104.1 1343.34  1153.8  1344.7  1213.4 1358.55
  1292.8 1379.84  1302.8 1384.14  1342.5 1385.42  1362.4  1392.4  1431.9 1406.23
#Mann= 3 , 0 , 0
       0      .1       0   671.3    .045       0     691      .1       0
Bank Sta=671.3,691
XS Rating Curve= 0 ,0
Exp/Cntr=0.3,0.1

Type RM Length L Ch R = 1 ,10455.6 ,929.4,940.3,943.8
XS GIS Cut Line= 4
     1865668.958      409854.919     1864929.321      409821.046
     1864766.127      409845.351     1864252.238      409959.934
#Sta/Elev= 30
       0 1425.76      79 1413.78   227.1 1379.42     306  1362.9     464 1340.57
     543 1326.95   631.8 1317.61     691 1308.72   759.8 1308.37   788.9 1310.12
   825.3 1307.66   837.5  1306.6   840.3 1306.73   847.2 1307.06   856.9 1310.23
   895.7  1327.7   905.4 1329.58   935.2 1330.48     965 1337.28  1084.2  1358.1
  1143.8  1371.1  1153.8  1373.9  1173.6 1382.54  1203.4 1385.56  1213.4 1393.44
  1223.3 1397.61  1372.3 1441.92  1392.2 1451.28    1412 1466.05  1431.9 1472.28
#Mann= 3 , 0 , 0
       0      .1       0   825.3    .045       0   840.3      .1       0
Bank Sta=825.3,840.3
XS Rating Curve= 0 ,0
Exp/Cntr=0.3,0.1

Type RM Length L Ch R = 1 ,9515.3  ,806.8,799.6,794.1
XS GIS Cut Line= 3
     1865795.903      409086.689     1865061.916      409079.615
      1864385.57      409129.564
#Sta/Elev= 30
       0 1412.17    19.8 1408.26    49.6 1396.74    89.3 1386.29     129 1377.21
   188.5 1367.66   228.1 1361.91   257.9 1359.13   386.8 1337.64   515.8 1318.48
   565.4 1312.58   714.2 1302.82     734  1300.1   735.2 1300.33   750.2 1303.84
   763.9 1307.95   773.9    1313   803.8 1332.95   813.8 1334.98   933.5 1343.55
   943.5 1344.76   963.4  1350.1  1003.3 1350.61  1043.2 1357.74    1113 1361.64
    1133 1366.76  1202.8 1376.29  1312.5 1396.64  1372.3 1410.11  1412.2 1417.78
#Mann= 3 , 0 , 0
       0      .1       0   735.2    .045       0   750.2      .1       0
Bank Sta=735.2,750.2
XS Rating Curve= 0 ,0
Exp/Cntr=0.3,0.1

Type RM Length L Ch R = 1 ,8715.7  ,593,588.3,582.7
XS GIS Cut Line= 3
     1865750.988      408289.421      1865073.26      408353.113
     1864353.162      408600.799
#Sta/Elev= 30
       0  1473.5    59.2 1460.69   118.4 1452.45   157.8 1444.39   197.3 1433.98
   246.6  1429.6   345.3 1412.32   384.8 1390.73   503.1 1351.03   621.5 1317.08
   769.7 1293.56   818.7 1290.71   819.2  1290.7   833.7 1290.84   858.7 1293.15
   868.6 1295.83   878.5 1300.71   888.4 1312.24   898.3 1320.16   937.8 1332.06
   967.5 1343.21  1036.7 1360.04  1076.3 1367.66  1096.1 1375.31    1106 1377.47
  1135.6 1377.77  1145.5 1380.08  1165.3 1388.72  1293.9 1423.01  1442.2 1472.88
#Mann= 3 , 0 , 0
       0      .1       0   818.7    .045       0   833.7      .1       0
Bank Sta=818.7,833.7
XS Rating Curve= 0 ,0
Exp/Cntr=0.3,0.1

Type RM Length L Ch R = 1 ,8127.4  ,417.2,403.3,389.3
XS GIS Cut Line= 4
      1865529.75      407502.333     1864959.438      407809.625
     1864808.396      407905.979     1864386.521      408379.938
#Sta/Elev= 30
       0 1417.27    39.9 1409.79    79.7 1408.88    89.7 1406.93   169.4 1381.78
   259.1 1358.54     299  1353.3   508.3 1334.34   528.2 1330.77   538.2 1327.33
   558.1 1315.98   568.1 1311.86     608 1301.72   647.8 1294.71   677.7 1287.47
   707.6 1286.71   726.2  1284.3   737.4  1283.4   741.2    1284   757.3  1286.4
     827 1289.98   856.7 1295.34   876.6 1302.54   896.4 1316.66   926.1 1329.34
  1035.2 1356.28  1074.8 1368.81  1203.7 1388.34  1352.4 1413.02  1461.5 1434.28
#Mann= 3 , 0 , 0
       0      .1       0   726.2    .045       0   741.2      .1       0
Bank Sta=726.2,741.2
XS Rating Curve= 0 ,0
Exp/Cntr=0.3,0.1

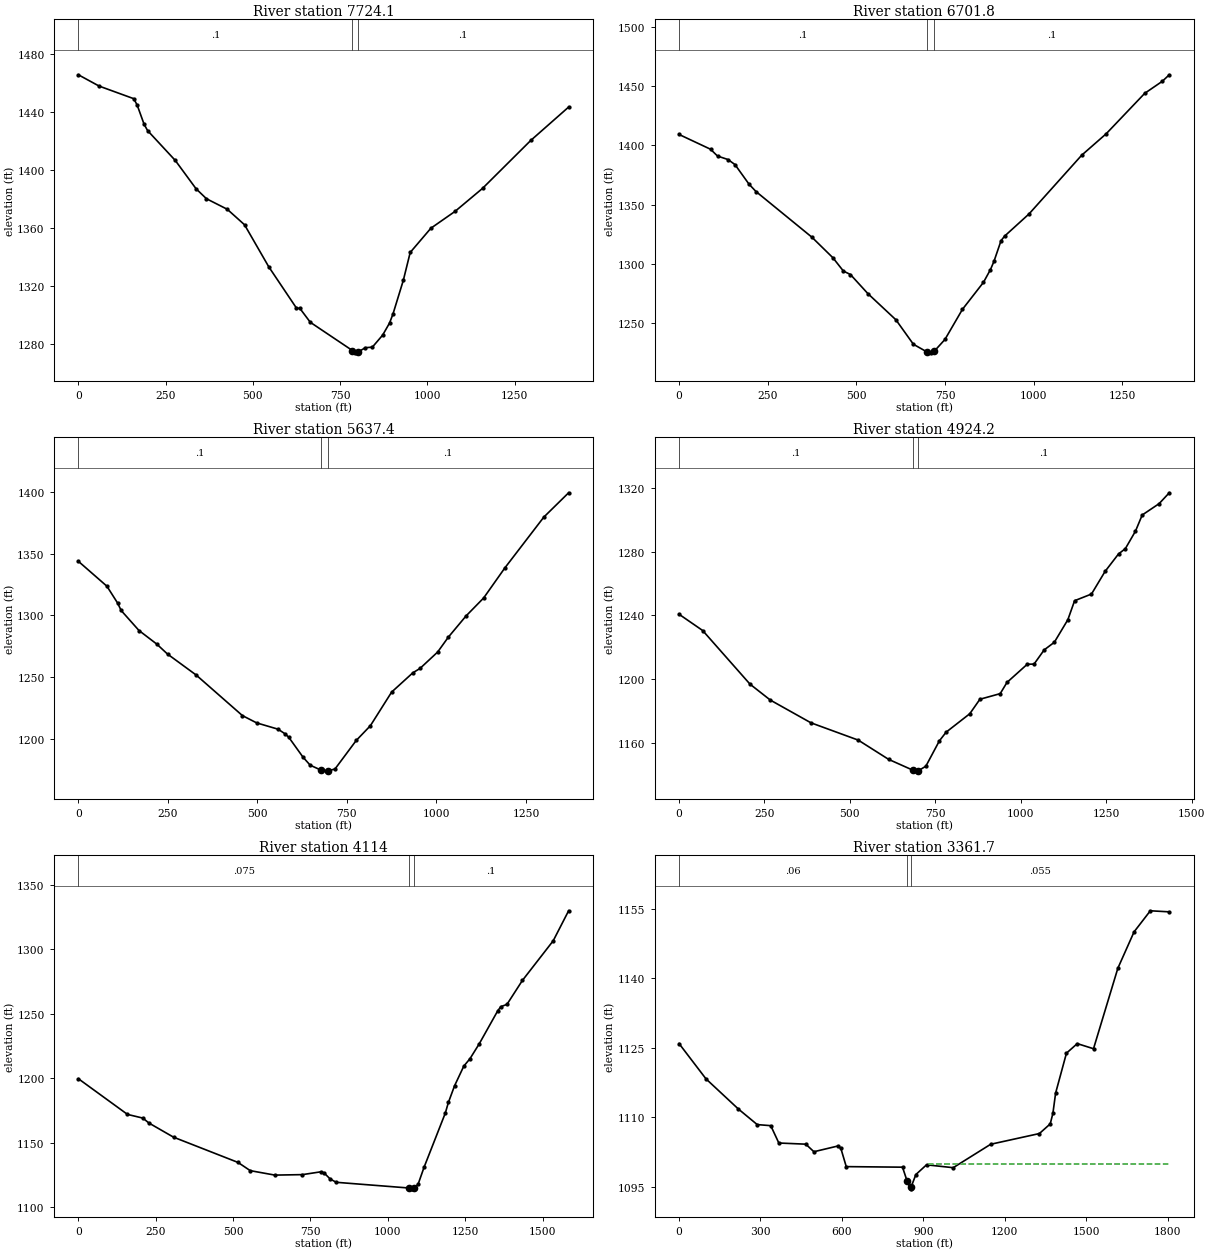
Type RM Length L Ch R = 1 ,7724.1  ,1020.6,1022.2,1023.8
XS GIS Cut Line= 3
     1864671.031      407003.649     1864604.925      407674.835
     1864288.558      408332.845
#Sta/Elev= 30
       0 1465.86    59.5 1458.04   158.7 1449.33   168.6 1444.84   188.4 1431.58
   198.4 1427.26   277.7 1406.62   337.2 1387.06     367 1380.16   426.5 1372.89
   476.1 1362.16   545.5 1333.09   624.8 1304.57   634.8  1304.3   664.5 1294.74
   785.1 1275.22   792.8 1273.62   800.1 1274.04   822.4 1277.19   842.2 1277.54
   871.8 1285.88   891.5 1294.21   901.4 1300.48     931 1323.76   950.7 1343.01
  1009.9 1359.76    1079 1371.38  1157.9 1387.31    1296 1420.44  1404.6 1443.54
#Mann= 3 , 0 , 0
       0      .1       0   785.1    .045       0   800.1      .1       0
Bank Sta=785.1,800.1
XS Rating Curve= 0 ,0
Exp/Cntr=0.3,0.1

Type RM Length L Ch R = 1 ,6701.8  ,1072.4,1064.5,1056.5
XS GIS Cut Line= 3
     1863990.247      406800.972     1863669.517      407401.014
     1863308.721       408002.79
#Sta/Elev= 30
       0 1409.15    88.8 1396.68   108.5 1390.93     138 1387.99   157.8 1383.71
   197.2 1367.24   216.9 1360.99   374.7  1322.4   433.9 1305.04   463.4 1293.84
   483.2 1290.94   532.5 1274.79   611.4 1252.72   660.7 1232.07   700.2 1225.39
     710 1224.84   719.3 1226.15   749.6 1236.13     799 1261.58   858.3 1284.38
     878 1295.14   887.9 1302.11   907.7 1319.46   917.6 1323.29   986.7 1342.08
    1135  1391.6  1204.2 1409.74  1312.8 1443.86  1362.3    1454    1382 1459.51
#Mann= 3 , 0 , 0
       0      .1       0   700.2    .045       0   719.3      .1       0
Bank Sta=700.2,719.3
XS Rating Curve= 0 ,0
Exp/Cntr=0.3,0.1

Type RM Length L Ch R = 1 ,5637.4  ,717.4,713.1,708.9
XS GIS Cut Line= 3
     1862900.885      406277.711     1862752.238      406907.851
     1862610.149      407615.353
#Sta/Elev= 30
       0    1344    79.7 1323.77   109.6 1310.07   119.5 1304.04   169.3 1287.78
   219.1 1276.72     249 1268.64   328.7 1251.68   458.2 1218.65     498 1212.73
   557.8 1207.61   577.7 1203.75   587.7    1201   627.5 1184.84   647.4 1178.38
   677.1 1174.42   696.9 1173.79   716.6 1175.26   775.9 1198.44   815.5 1210.44
   874.8 1237.75   934.1 1253.44   953.9 1256.93  1003.3 1270.28    1033 1282.32
  1082.4 1299.53  1131.8 1314.21  1191.1 1338.65  1299.9 1379.92  1369.1 1399.66
#Mann= 3 , 0 , 0
       0      .1       0   677.1    .045       0   696.9      .1       0
Bank Sta=677.1,696.9
XS Rating Curve= 0 ,0
Exp/Cntr=0.3,0.1

Type RM Length L Ch R = 1 ,4924.2  ,810.7,810.2,807.9
XS GIS Cut Line= 3
     1862075.155      406216.879     1862052.902       406928.79
     1862022.724      407650.387
#Sta/Elev= 30
       0 1240.75    69.2 1230.54   207.7 1196.94   267.1 1186.97   385.8 1172.74
   524.3 1161.89   613.3 1149.82   684.7    1143   699.7 1142.63   722.2 1145.52
   761.7 1161.38   781.5 1166.85   850.8 1178.41   880.4 1187.48   939.8    1191
   959.6 1198.02    1019 1209.43  1038.8  1209.5  1068.4 1218.39  1098.1 1223.16
  1137.7  1237.3  1157.5 1249.23  1206.9  1253.4  1246.5 1267.52  1286.1 1278.55
  1305.9  1281.8  1335.6  1292.8  1355.3 1302.92  1404.8 1310.03  1434.5 1316.84
#Mann= 3 , 0 , 0
       0      .1       0   684.7    .045       0   699.7      .1       0
Bank Sta=684.7,699.7
XS Rating Curve= 0 ,0
Exp/Cntr=0.3,0.1

Type RM Length L Ch R = 1 ,4114    ,745.3,752.3,760.3
XS GIS Cut Line= 4
     1861457.099      406098.823     1861330.679       407022.54
      1861349.46      407255.073     1861387.655       407671.74
#Sta/Elev= 30
       0 1199.54   158.7 1171.87   208.3 1169.01   228.1 1165.16   307.5 1154.21
   515.8 1134.63   555.4 1128.25   634.8  1124.8     724 1125.17   783.6 1127.36
   793.5 1126.58   813.3 1121.85   833.1 1119.22  1068.8 1114.78  1078.1 1114.15
  1083.8 1114.53  1097.6 1117.66    1117 1130.92  1185.5 1172.84  1195.5  1181.1
  1215.4 1194.01  1245.3  1209.3  1265.2 1215.04  1295.1 1226.56  1354.9 1252.17
  1364.9  1255.4  1384.8 1257.19  1434.6 1275.73  1534.2  1306.5    1584 1329.76
#Mann= 3 , 0 , 0
       0    .075       0  1068.8    .045       0  1083.8      .1       0
Bank Sta=1068.8,1083.8
XS Rating Curve= 0 ,0
Exp/Cntr=0.3,0.1

Type RM Length L Ch R = 1 ,3361.7  ,91.8,91.8,91.8
XS GIS Cut Line= 4
     1860957.099      406258.546     1860707.099      406907.851
     1860616.821      407310.629     1860616.821      408008.546
#Sta/Elev= 30
       0 1125.93    99.4 1118.31   218.7 1111.81   288.2 1108.45     338 1108.22
   367.8 1104.48   467.2 1104.23     497  1102.6   586.4 1103.85   596.4 1103.31
   616.2 1099.39   823.5 1099.27   840.2 1096.33     853  1094.6   855.2 1094.99
   872.7 1097.68     912 1099.78  1010.3 1099.16  1148.4 1104.21  1327.9 1106.52
  1367.8  1108.6  1377.7 1110.89  1387.7 1115.25  1427.6 1123.85  1467.5 1125.91
  1527.3 1124.81    1617 1142.16  1676.8 1150.01  1736.7 1154.55  1806.5 1154.32
#Mann= 3 , 0 , 0
       0     .06       0   840.2    .045       0   855.2    .055       0
#XS Ineff= 2 , 0
                          921.94         1099.93
Permanent Ineff=
       F       F
Bank Sta=840.2,855.2
XS Rating Curve= 0 ,0
Exp/Cntr=0.3,0.1

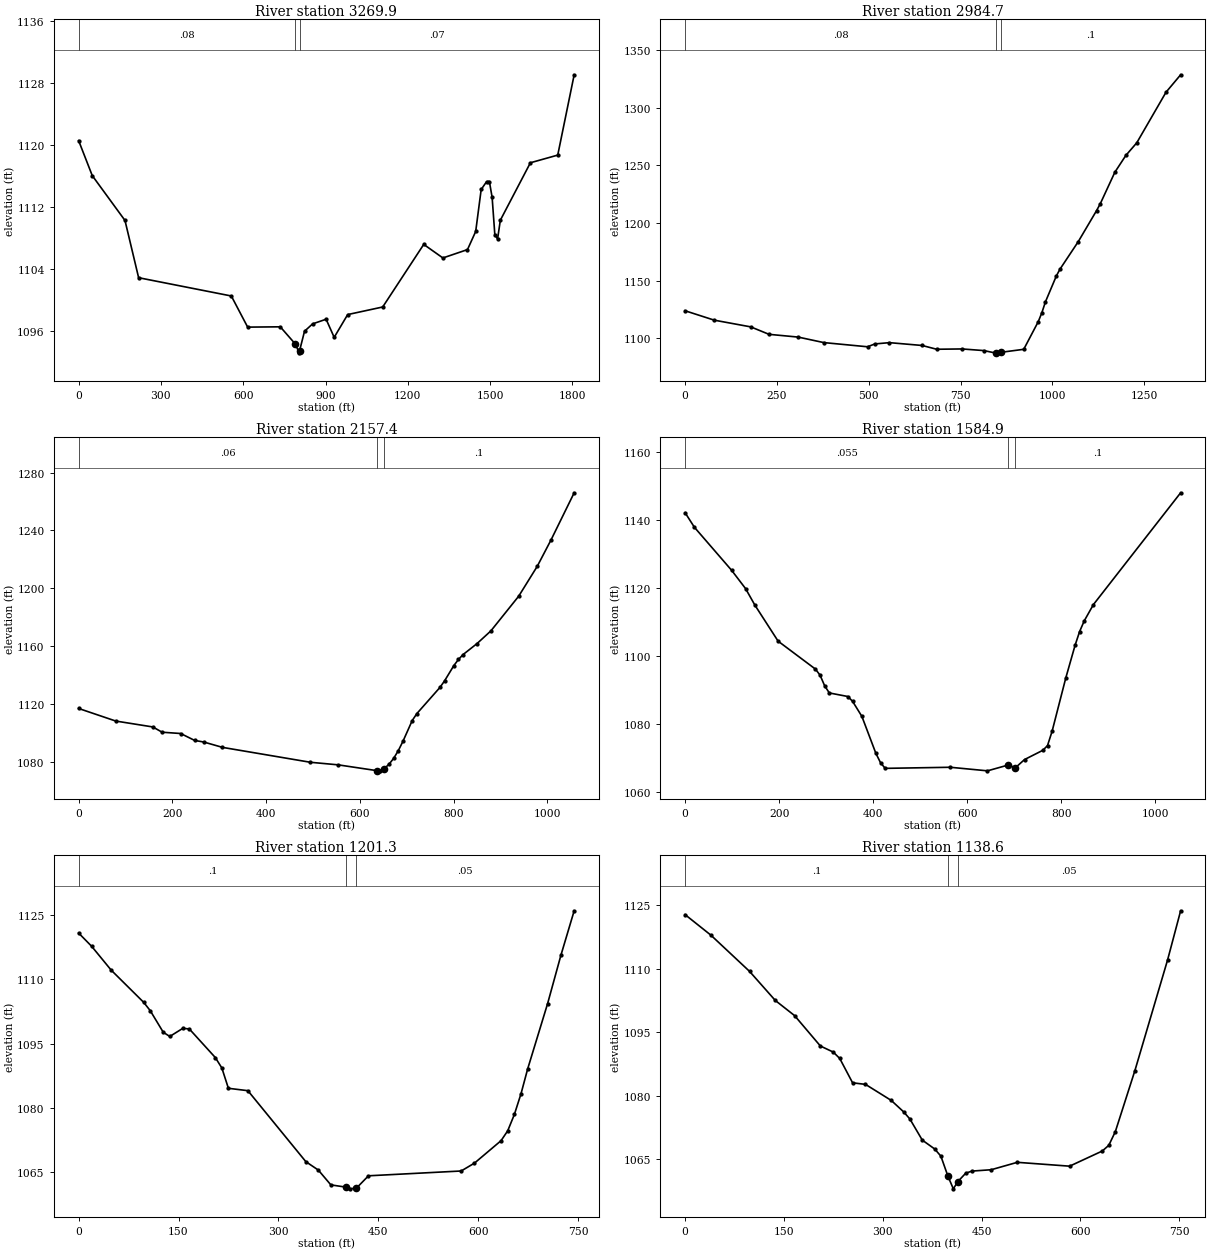
Type RM Length L Ch R = 1 ,3269.9  ,272.5,285.3,298.2
XS GIS Cut Line= 4
     1860859.877      406275.907     1860609.877      406925.212
     1860519.599       407327.99     1860519.599      408025.907
#Sta/Elev= 30
       0 1120.56    49.7 1116.04     169 1110.25   218.7 1102.86   556.6  1100.5
   616.2 1096.48   735.1 1096.52   790.4 1094.28   803.9 1093.16   805.4 1093.42
   823.5 1095.95     853  1096.9   902.2  1097.5   931.6 1095.16   980.8  1098.1
  1108.5 1099.08  1258.1 1107.16  1327.9 1105.41  1417.6 1106.49  1447.5 1108.83
  1467.5 1114.25  1487.4 1115.27  1497.4 1115.28  1507.4 1113.24  1517.3  1108.4
  1527.3 1107.86  1537.3 1110.28  1646.9  1117.7  1746.6 1118.69  1806.5 1129.06
#Mann= 3 , 0 , 0
       0     .08       0   790.4    .045       0   805.4     .07       0
#XS Ineff= 2 , 0
                          902.16         1097.49
Permanent Ineff=
       F       F
Bank Sta=790.4,805.4
XS Rating Curve= 0 ,0
Exp/Cntr=0.3,0.1

Type RM Length L Ch R = 1 ,2984.7  ,817.9,827.2,835.7
XS GIS Cut Line= 4
     1860860.897      406225.088     1860526.543      406706.462
      1860224.46      407005.073     1859960.571      407216.879
#Sta/Elev= 30
       0 1123.93    79.5 1115.77   178.8 1109.95   228.5 1103.49     308 1101.09
   377.5 1096.33   496.7 1092.69   516.6 1095.15   556.3 1096.27   645.4 1093.82
   684.9 1090.54     754 1090.81   813.3 1089.39   842.9 1087.43   846.3  1087.5
   861.3 1087.95     922 1090.49   961.5 1114.46   971.4 1122.26   981.2 1131.77
  1010.9  1154.2  1020.8 1160.09  1070.6 1183.98  1120.3 1210.82  1130.3 1216.72
  1170.1 1244.12    1200 1258.68  1229.8 1269.67  1309.4 1313.54  1349.2 1328.66
#Mann= 3 , 0 , 0
       0     .08       0   846.3    .045       0   861.3      .1       0
Bank Sta=846.3,861.3
XS Rating Curve= 0 ,0
Exp/Cntr=0.3,0.1

Type RM Length L Ch R = 1 ,2157.4  ,572.3,572.5,572.3
XS GIS Cut Line= 3
      1860661.96      405858.372      1860349.46      406007.677
     1859696.682      406288.927
#Sta/Elev= 30
       0 1116.76    79.2 1108.05   158.3 1103.96   178.1 1100.31   217.7 1099.42
   247.4 1094.64   267.2 1093.51   306.8 1089.82   494.4  1079.5   553.6 1077.72
   635.8 1073.73   642.5 1073.57   650.8 1074.75   662.2 1078.17   672.1 1082.25
     682 1087.59   691.9 1094.06   711.6 1108.38   721.5 1113.21   770.8 1131.34
   780.7 1135.92   800.4 1146.45   810.3 1150.73   820.2 1154.11   849.8 1161.67
   879.4 1170.47   938.7 1194.48   978.2 1215.13  1007.8 1233.51  1057.1 1266.12
#Mann= 3 , 0 , 0
       0     .06       0   635.8    .045       0   650.8      .1       0
Bank Sta=635.8,650.8
XS Rating Curve= 0 ,0
Exp/Cntr=0.3,0.1

Type RM Length L Ch R = 1 ,1584.9  ,382.3,383.6,383.4
XS GIS Cut Line= 3
     1860491.821      405345.351      1859849.46      405604.032
     1859521.335      405755.073
#Sta/Elev= 30
       0 1142.07    19.8 1137.78    98.9 1125.13   128.6 1119.74   148.4 1114.88
   197.8 1104.28     277 1096.08   286.9  1094.3   296.8 1091.14   306.7 1089.05
   346.2    1088   356.1 1086.59   375.9 1082.16   405.6  1071.3   415.5 1068.55
   425.4 1066.87   563.9 1067.19     643 1066.14   687.2 1067.86   702.2 1067.04
   721.8 1069.46   760.8 1072.19   770.6 1073.56   780.4 1077.79   809.6 1093.52
   829.2 1103.05   838.9 1107.12   848.7 1110.25   868.2 1115.04  1053.7 1147.93
#Mann= 3 , 0 , 0
       0    .055       0   687.2    .045       0   702.2      .1       0
Bank Sta=687.2,702.2
XS Rating Curve= 0 ,0
Exp/Cntr=0.3,0.1

Type RM Length L Ch R = 1 ,1201.3  ,59.7,62.7,68.2
XS GIS Cut Line= 4
     1860300.849      405262.018     1859988.349      405246.393
     1859858.141      405267.226      1859565.08      405328.853
#Sta/Elev= 30
       0 1120.81    19.6 1117.71    48.9 1112.16    97.8 1104.64   107.6  1102.7
   127.1 1097.68   136.9  1096.7   156.4 1098.59   166.2 1098.46   205.3 1091.78
   215.1 1089.35   224.9 1084.62   254.2 1084.06   341.2 1067.52     360 1065.55
   378.8  1062.1   402.2 1061.56   407.1 1061.18   417.2 1061.35   435.3 1064.22
   574.5 1065.34   594.5 1067.18   634.4 1072.41   644.4 1074.71   654.4 1078.52
   664.4 1083.37   674.4 1089.16   704.3 1104.36   724.3 1115.64   744.2    1126
#Mann= 3 , 0 , 0
       0      .1       0   402.2    .045       0   417.2     .05       0
Bank Sta=402.2,417.2
XS Rating Curve= 0 ,0
Exp/Cntr=0.3,0.1

Type RM Length L Ch R = 1 ,1138.6  ,196.6,201.7,206.8
XS GIS Cut Line= 4
     1860300.849      405204.726     1859988.349      405189.101
     1859858.141      405209.934     1859555.315      405262.663
#Sta/Elev= 30
       0 1122.75    39.1 1117.91    97.8 1109.36   136.9 1102.49   166.2 1098.91
   205.3 1091.74   224.9  1090.3   234.7  1088.8   254.2 1083.05   273.8 1082.68
   312.9 1078.89   331.7 1076.19   341.2  1074.5     360 1069.52   378.8 1067.43
   388.2 1065.74   398.9 1061.01   407.1 1058.02   413.9 1059.73   425.9 1061.71
   435.3 1062.21   464.6 1062.53   504.2 1064.28   583.6 1063.37   633.2 1066.95
   643.1  1068.3     653 1071.53   682.7 1085.94   732.3 1112.06   752.1 1123.66
#Mann= 3 , 0 , 0
       0      .1       0   398.9    .045       0   413.9     .05       0
Bank Sta=398.9,413.9
XS Rating Curve= 0 ,0
Exp/Cntr=0.3,0.1

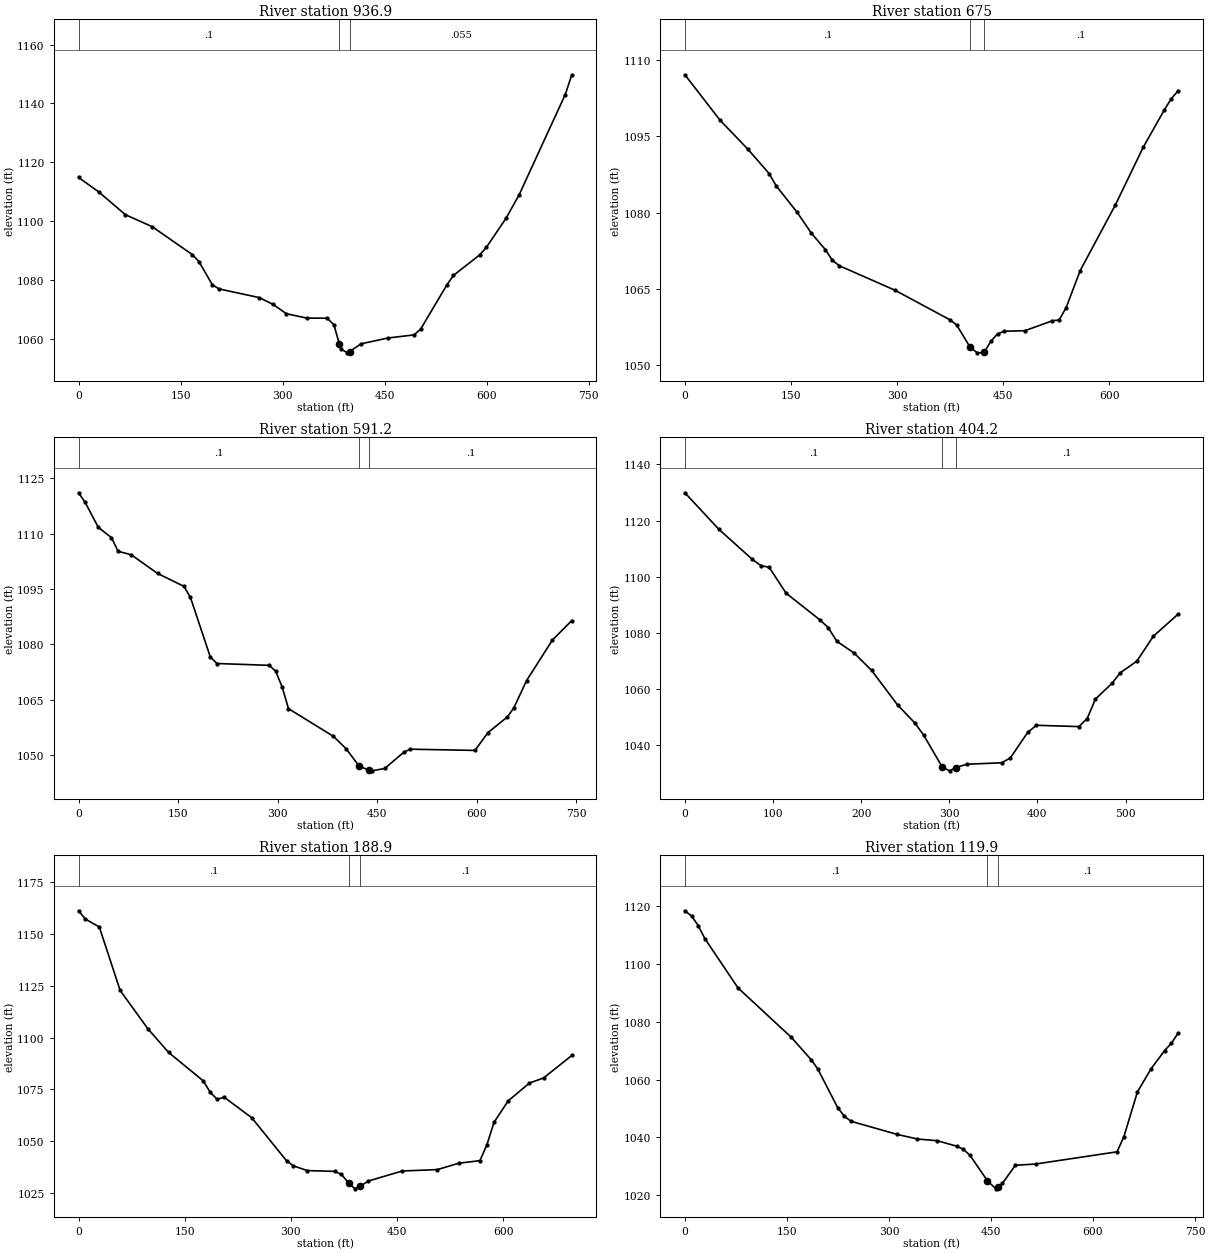
Type RM Length L Ch R = 1 ,936.9   ,234.7,262,288.9
XS GIS Cut Line= 4
     1860179.321      405062.365      1859934.53      405038.059
     1859745.251      405032.573     1859455.363      405024.171
#Sta/Elev= 30
       0 1114.84    29.5 1109.96    68.9 1102.18   108.2 1098.12   167.3 1088.62
   177.1 1086.24   196.8 1078.35   206.6 1076.95   265.9 1073.99   285.9 1071.71
   305.8 1068.51   335.7 1067.03   365.6 1066.99   375.6 1064.75   383.6 1058.14
   385.5 1056.57   395.5 1055.22   398.6 1055.63   415.4 1058.28   454.7 1060.25
   493.4 1061.32     503 1063.24   541.7 1078.32   551.4 1081.55     590 1088.52
   599.7 1091.06   628.7 1100.97     648 1108.96   715.7 1142.99   725.4 1149.73
#Mann= 3 , 0 , 0
       0      .1       0   383.6    .045       0   398.6    .055       0
Bank Sta=383.6,398.6
XS Rating Curve= 0 ,0
Exp/Cntr=0.3,0.1

Type RM Length L Ch R = 1 ,675     ,85.1,83.8,99.8
XS GIS Cut Line= 4
     1860135.918      405032.851     1859892.863      404920.004
     1859788.696      404680.421     1859625.502      404638.754
#Sta/Elev= 30
       0 1107.14    49.6  1098.2    89.3 1092.44   119.1 1087.67     129 1085.27
   158.8 1080.02   178.6 1075.97   198.5 1072.71   208.4  1070.6   218.4 1069.51
     297 1064.69   374.4 1058.89   384.1 1057.87     403 1053.53   413.1 1052.38
   422.8 1052.35  423.291052.464   432.5  1054.6   442.1 1056.09   451.8 1056.61
   480.8 1056.71   519.6 1058.67   529.2 1058.82   539.1 1061.25     559 1068.57
   608.5 1081.43   648.1 1092.85   677.8 1100.18   687.8 1102.42   697.6 1104.02
#Mann= 3 , 0 , 0
       0      .1       0     403    .045       0  423.29      .1       0
Bank Sta=403,423.29
XS Rating Curve= 0 ,0
Exp/Cntr=0.3,0.1

Type RM Length L Ch R = 1 ,591.2   ,213.8,186.9,142.6
XS GIS Cut Line= 4
     1860189.694      404981.332     1859946.639      404868.485
     1859842.472      404628.901     1859639.347      404561.193
#Sta/Elev= 30
       0  1121.1     9.9 1118.54    29.8 1111.72    49.6 1108.94    59.6 1105.23
    79.4  1104.3   119.1 1099.22   158.8 1095.73   168.7  1092.7   198.5 1076.61
   208.4  1074.8   287.3  1074.3     297 1072.73   306.7 1068.49   316.4 1062.56
   384.1 1055.04   403.4 1051.65   423.1  1046.9   438.1 1045.88   442.1 1045.69
   461.5 1046.33   490.5  1050.8   500.2 1051.56   597.4 1051.23   616.8 1056.03
     646 1060.28   655.7 1062.68   675.2 1070.19   714.1 1081.17   743.3 1086.45
#Mann= 3 , 0 , 0
       0      .1       0   423.1    .045       0   438.1      .1       0
Bank Sta=423.1,438.1
XS Rating Curve= 0 ,0
Exp/Cntr=0.3,0.1

Type RM Length L Ch R = 1 ,404.2   ,230.2,215.4,199.8
XS GIS Cut Line= 4
     1860191.474      404558.893     1860030.016      404539.796
     1859764.391      404531.115     1859635.918      404558.893
#Sta/Elev= 30
       0 1129.88    38.3 1116.95    76.5 1106.17    86.1 1103.97    95.6 1103.36
   114.8 1094.14     153 1084.67   162.6 1081.91   172.4    1077   192.1 1072.81
   211.8 1066.67   241.3 1054.37     261  1047.9   270.9 1043.62   292.1  1032.2
   300.4 1030.89   307.1 1032.07   320.1 1033.24   359.4 1033.76   369.3 1035.48
     389 1044.57   398.8 1047.11   447.1 1046.64   456.5  1049.5   465.9 1056.46
   484.7 1062.05   494.1 1065.81   512.8 1069.92   531.6 1078.81   559.8 1086.71
#Mann= 3 , 0 , 0
       0      .1       0   292.1    .045       0   307.1      .1       0
Bank Sta=292.1,307.1
XS Rating Curve= 0 ,0
Exp/Cntr=0.3,0.1

Type RM Length L Ch R = 1 ,188.9   ,69,69,69
XS GIS Cut Line= 4
     1860194.946      404239.448     1859868.557      404305.421
     1859760.918      404385.282     1859606.405      404555.421
#Sta/Elev= 30
       0 1161.29     9.8 1157.28    29.4 1153.43    58.8 1122.77    97.9 1104.27
   127.3 1092.77   176.3 1079.02   186.1 1073.46   195.9 1070.14   205.7 1071.16
   244.8 1061.17   293.8 1040.43   303.6 1037.95   323.2 1035.66   361.7 1035.28
   371.3 1033.85   382.2 1029.43   390.4 1026.84   397.2 1027.99   409.6 1030.64
   457.4 1035.47     507 1036.15     537 1039.23     567 1040.47   576.9 1048.17
   586.9 1058.99   606.9 1069.37   636.9 1077.98   656.9 1080.45   696.8 1091.33
#Mann= 3 , 0 , 0
       0      .1       0   382.2    .045       0   397.2      .1       0
Bank Sta=382.2,397.2
XS Rating Curve= 0 ,0
Exp/Cntr=0.3,0.1

Type RM Length L Ch R = 1 ,119.9   ,110.5,119.9,128.4
XS GIS Cut Line= 4
     1860196.682      404159.587     1859844.252      404239.448
     1859736.613      404319.309     1859582.099      404489.448
#Sta/Elev= 30
       0 1118.25     9.8 1116.43    19.5 1113.16    29.3 1108.65    78.1 1091.61
   156.3  1074.6   185.6 1066.86   195.3 1063.67   224.6  1050.3   234.4 1047.34
   244.2 1045.59   312.5 1041.04   341.8 1039.48   370.9 1038.89   399.7 1036.99
   409.2 1035.92   418.8 1033.95   444.6  1025.1   457.1 1022.28   459.6 1022.77
   466.7 1024.15   485.8 1030.42   515.4 1030.84   635.3 1035.06   645.3 1040.26
   665.3 1055.76   685.2 1063.68   705.2    1070   715.2 1072.54   725.2 1076.08
#Mann= 3 , 0 , 0
       0      .1       0   444.6    .045       0   459.6      .1       0
Bank Sta=444.6,459.6
XS Rating Curve= 0 ,0
Exp/Cntr=0.3,0.1

Chan Stop Cuts=-1
Use User Specified Reach Order=0
Composite Channel Slope=5